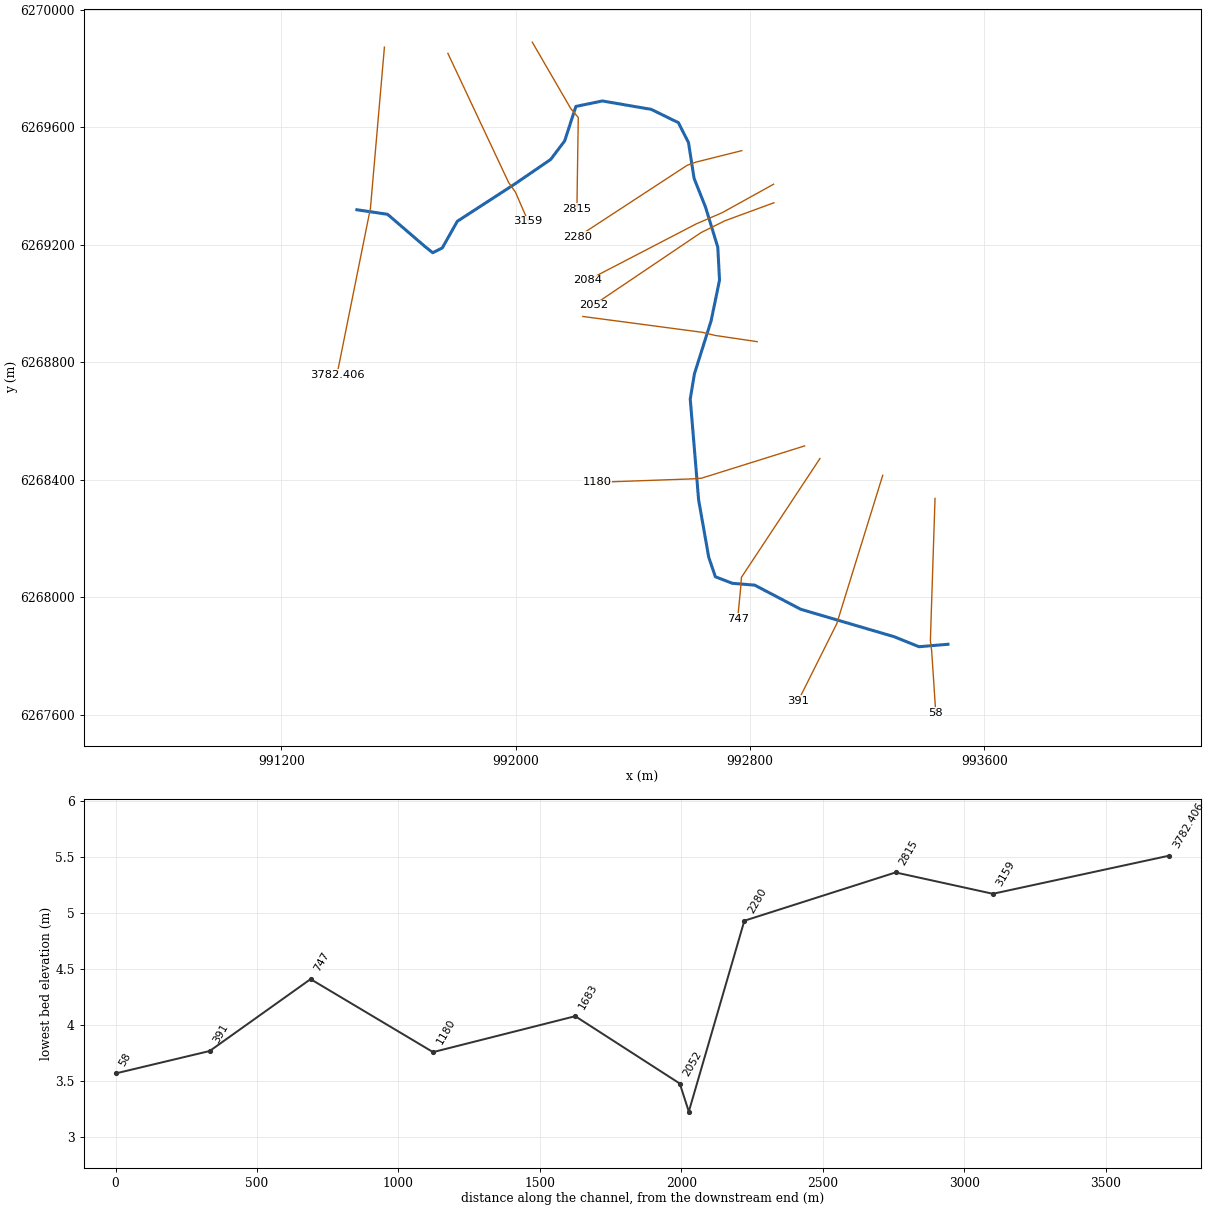
--- test3.prj (project) ---

Proj Title=test3
Current Plan=p01
Default Exp/Contr=0.3,0.1
SI Units
Geom File=g01
Flow File=f01
Flow File=f02
Plan File=p01
Y Axis Title=Elevation
X Axis Title(PF)=Main Channel Distance
X Axis Title(XS)=Station
BEGIN DESCRIPTION:
END DESCRIPTION:
DSS Export Rating Curves= 0
DSS Export Rating Curve Sorted= 0
DSS Export Volume Flow Curves= 0
DXF OffsetX= 0
DXF OffsetY= 0
DXF ScaleX= 1
DXF ScaleY= 10

--- test3.p01 (plan) ---

Plan Title=Plan 01
Program Version=5.00
Short Identifier=Plan 01
Geom File=g01
Flow File=f02
Mixed Flow
K Sum by GR= 0
Std Step Tol= 0.003
Critical Tol= 0.003
Num of Std Step Trials= 20
Max Error Tol= 0.1
Flow Tol Ratio= 0.001
Split Flow NTrial= 30
Split Flow Tol= 0.006
Split Flow Ratio= 0.02
Log Output Level= 0
Friction Slope Method= 1
Unsteady Friction Slope Method= 2
Unsteady Bridges Friction Slope Method= 1
Parabolic Critical Depth
Global Vel Dist= 0 , 0 , 0
Global Log Level= 0
CheckData=Vrai
Encroach Param=-1 ,0,0, 0
Computation Interval=1MIN
Output Interval=1HOUR
Instantaneous Interval=1HOUR
Mapping Interval=1HOUR
Run HTab= 0
Run UNet= 0
Run Sediment= 0
Run PostProcess= 0
Run WQNet= 0
Run RASMapper=-1
UNET Theta= 1
UNET Theta Warmup= 1
UNET ZTol= 0.006
UNET ZSATol= 0.006
UNET MxIter= 20
UNET Max Iter WO Improvement= 0
UNET MaxInSteps= 0
UNET DtIC= 0
UNET DtMin= 0
UNET MaxCRTS= 20
UNET WFStab= 2
UNET SFStab= 1
UNET WFX= 1
UNET SFX= 1
UNET DSS MLevel= 4
UNET Pardiso=0
UNET DZMax Abort= 30
UNET Use Existing IB Tables=-1
UNET Froude Reduction=Faux
UNET Froude Limit= 0.8
UNET Froude Power= 4
UNET Time Slicing=0,0, 5
UNET Junction Losses=0
UNET D1 Cores= 0
UNET D2 Coriolis=0
UNET D2 Cores= 0
UNET D2 Theta= 1
UNET D2 Theta Warmup= 1
UNET D2 Z Tol= 0.003
UNET D2 Volume Tol= 0.003
UNET D2 Max Iterations= 20
UNET D2 Equation= 0
UNET D2 RampUpFraction=0.1
UNET D2 TimeSlices= 1
UNET D2 BCVolumeCheck=0
UNET D1D2 MaxIter= 0
UNET D1D2 ZTol=0.003
UNET D1D2 QTol=0.1
UNET D1D2 MinQTol=0.03
Write IC File= 0
Write IC File at Fixed DateTime=0
Write IC File at Sim End=0
Echo Input=Faux
Echo Parameters=Faux
Echo Output=Faux
Write Detailed= 0
HDF Write Warmup=0
HDF Write Time Slices=0
HDF Flush=0
HDF Face Node Velocities=0
HDF Compression= 1
HDF Chunk Size= 1
HDF Spatial Parts= 1
HDF Use Max Rows=0
HDF Fixed Rows= 1
Calibration Method= 0
Calibration Iterations= 20
Calibration Max Change=0.05
Calibration Tolerance=0.2
Calibration Maximum=1.5
Calibration Minimum=0.5
Calibration Optimization Method= 1
WQ AD Non Conservative
WQ ULTIMATE=-1
WQ Max Comp Step=1HOUR
WQ Output Interval=15MIN
WQ Output Selected Increments= 0
WQ Output face flow=0
WQ Output face velocity=0
WQ Output face area=0
WQ Output face dispersion=0
WQ Output cell volume=0
WQ Output cell surface area=0
WQ Output cell continuity=0
WQ Output cumulative cell continuity=0
WQ Output face conc=0
WQ Output face dconc_dx=0
WQ Output face courant=0
WQ Output face peclet=0
WQ Output face adv mass=0
WQ Output face disp mass=0
WQ Output cell mass=0
WQ Output cell source sink temp=0
WQ Output nsm pathways=0
WQ Output nsm derived pathways=0
WQ Output MaxMinRange=-1
WQ Daily Max Min Mean=-1
WQ Daily Range=0
WQ Daily Time=0
WQ Create Restart=0
WQ Fixed Restart=0
WQ System Summary=0
WQ Write To DSS=0
WQ Use Fixed Temperature=0
Sorting and Armoring Iterations= 10
XS Update Threshold= 0.02
Bed Roughness Predictor= 0
Hydraulics Update Threshold= 0.02
Energy Slope Method= 1
Volume Change Method= 1
Sediment Retention Method= 0
XS Weighting Method= 0
Number of US Weighted Cross Sections= 1
Number of DS Weighted Cross Sections= 1
Upstream XS Weight=0
Main XS Weight=1
Downstream XS Weight=0
Number of DS XS's Weighted with US Boundary= 1
Upstream Boundary Weight= 1
Weight of XSs Associated with US Boundary= 0
Number of US XS's Weighted with DS Boundary= 1
Downstream Boundary Weight= 0.5
Weight of XSs Associated with DS Boundary= 0.5
Percentile Method= 0
Sediment Output Level= 4
Mass or Volume Output= 0
Output Increment Type= 1
Profile and TS Output Increment= 1
XS Output Flag= 0
XS Output Increment= 10
Write Gradation File= 0
Read Gradation Hotstart= 0
Write HDF5 File= 1
Write DSS Sediment File= 0
SV Curve= 0
Specific Gage Flag= 0

--- test3.f02 (steady flow) ---

Flow Title=Flow 02
Program Version=5.00
Number of Profiles= 1
Profile Names=PF 1
River Rch & RM=argens,1               ,3782.406
     500
Boundary for River Rch & Prof#=argens,1               , 1
Up Type= 3
Up Slope=0.01
Dn Type= 3
Dn Slope=0.01
DSS Import GetInterval= 0
DSS Import GetPeak= 0
DSS Import FillOption= 0

--- test3.g01 (geometry) ---

Geom Title=test3
Program Version=5.00

River Reach=argens          ,1
Reach XY= 30
991458.1534845696269318.84527594991562.917308157  6269303.368802
 991689.110095666269195.03348443991717.1037991886269172.58742902
991749.8254934226269189.08099445 991801.01690722 6269279.5588421
991999.4879679256269407.95099599992120.0703699656269490.27698727
992167.6902897786269553.37338102992205.7864739396269670.43398396
992296.2640732726269689.09015248992462.933792616 6269660.5182006
992555.7926362516269615.27927677992590.3170781156269547.42089104
 992609.365046046269425.99009552992648.6514798856269327.17876191
992690.3189097216269191.46199044992696.2713996986269079.55517888
 992667.699447816268941.45741143992610.5555440356268760.50171614
992596.2695680916268674.78586047992624.8415199796268331.92243782
992659.3659618436268136.68076659992681.9854237546268070.01287885
 992739.767132796268047.80928321992816.5116972256268041.44092697
992973.6574326076267959.29656529993292.5758295526267865.95133717
993377.2362530196267831.91327979 993476.047586636267840.24676576

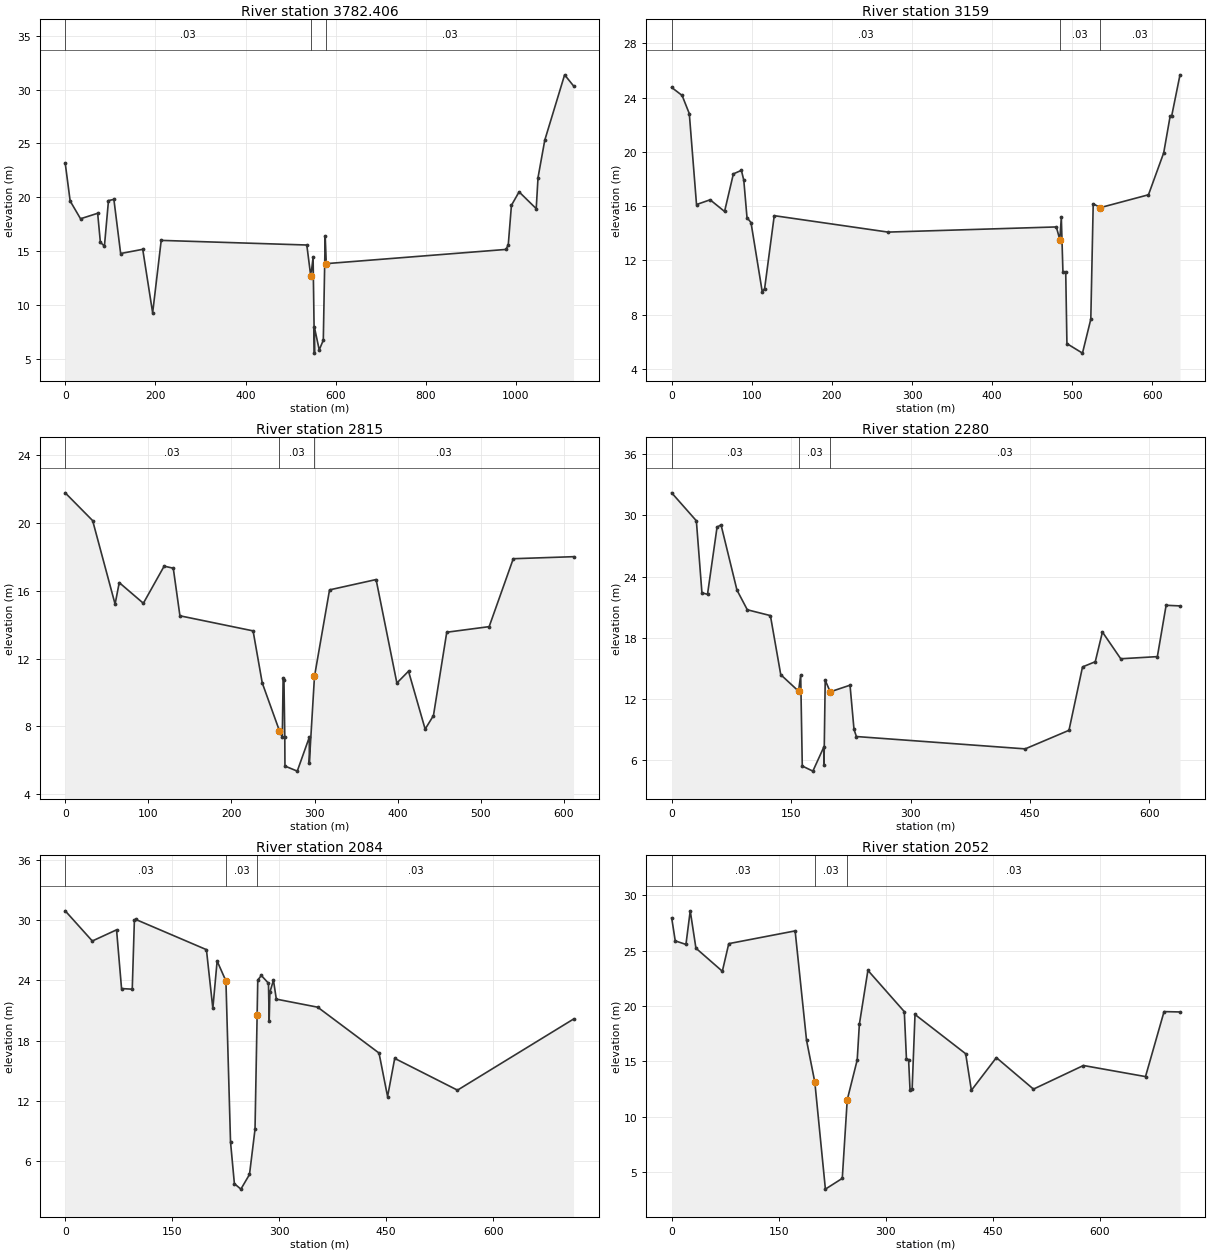
Type RM Length L Ch R = 1 ,3782.406,470.629,623.803,607.972
XS GIS Cut Line= 4
991552.2028261996269872.42684376        991504.5      6269324.53
        991499.2      6269298.21991390.2950988366268758.12072015
#Sta/Elev= 30
       0   23.17      11   19.65      34      18      72   18.51      78   15.82
      87   15.45      96   19.69     108    19.8     123   14.77     172   15.16
     194    9.25     213   15.99     536   15.56 544.893  12.641  549.97   14.41
 552.968    5.51 552.968    7.91 563.567    5.81 572.615    6.71 576.818   16.41
 579.192  13.829     978   15.15     983    15.6     990   19.25    1007    20.5
    1045   18.94    1049   21.83    1064   25.31    1108   31.381127.778   30.35
#Mann= 3 , 0 , 0
       0     .03       0 544.893     .03       0 579.192     .03       0
Bank Sta=544.893,579.192
XS Rating Curve= 0 ,0
Exp/Cntr=0.3,0.1

Type RM Length L Ch R = 1 ,3159    ,316.312,343.894,256.776
XS GIS Cut Line= 4
991768.8734613476269850.99787985       991976.37      6269411.26
       991999.51      6269378.89992042.688000269 6269279.5588421
#Sta/Elev= 30
       0   24.75      13   24.16      22   22.82      31   16.12      48   16.47
      66   15.61      77   18.38      87   18.64      90   17.91      94   15.16
      99   14.79     113     9.7     116    9.93     128    15.3     270   14.09
     480   14.47 484.345  13.538 486.235   15.17 488.236   11.17 491.726   11.17
 493.231    5.87 512.628    5.17 523.028    7.67 526.025   16.17 535.124  15.896
     595   16.84     614   19.93     622   22.62     624   22.66 634.335   25.68
#Mann= 3 , 0 , 0
       0     .03       0 484.345     .03       0 535.124     .03       0
Bank Sta=484.345,535.124
XS Rating Curve= 0 ,0
Exp/Cntr=0.3,0.1

Type RM Length L Ch R = 1 ,2815    ,625.5,534.427,356.865
XS GIS Cut Line= 4
992056.973976213 6269889.0938157       992188.26      6269663.36
         992214.      6269632.74992209.3577196146269322.41676993
#Sta/Elev= 30
       0   21.79      33   20.15      60   15.22      65   16.49      94   15.27
     119   17.46     130   17.34     138   14.53     226   13.64     237   10.57
 257.596   7.754 261.136    7.36 262.137   10.86  263.13   10.76 264.138    7.36
  264.33    5.66 279.135    5.36 293.636    7.36 293.636    5.86 299.852  10.949
 317.971   16.06 373.971   16.67 398.971   10.56 412.971   11.26 432.971    7.84
 442.971    8.64 458.971   13.56 509.971   13.89 538.971    17.9 611.466   18.02
#Mann= 3 , 0 , 0
       0     .03       0 257.596     .03       0 299.852     .03       0
Bank Sta=257.596,299.852
XS Rating Curve= 0 ,0
Exp/Cntr=0.3,0.1

Type RM Length L Ch R = 1 ,2280    ,177.6,196.356,182.629
XS GIS Cut Line= 4
992772.4632713986269520.03943715       992615.24      6269480.84
       992586.23      6269470.49  992212.9292136 6269227.1769303
#Sta/Elev= 30
       0    32.2      31   29.46      38   22.41      45   22.25      57   28.84
      62   29.06      82   22.67      95   20.74     124   20.17     137   14.38
 159.312  12.769 162.036   14.33 164.032    5.43 177.336    4.93 191.328    7.33
 191.328    5.53 192.837   13.83 199.157  12.701     224   13.35     229    9.02
     232    8.32     444    7.11     499    8.93     516   15.14     532   15.65
     541   18.56     564   15.94     610   16.15     621   21.18 638.432   21.12
#Mann= 3 , 0 , 0
       0     .03       0 159.312     .03       0 199.157     .03       0
Bank Sta=159.312,199.157
XS Rating Curve= 0 ,0
Exp/Cntr=0.3,0.1

Type RM Length L Ch R = 1 ,2084    ,36.081,31.762,37.649
XS GIS Cut Line= 4
992880.798588972 6269405.7516296       992705.12      6269308.79
       992616.46      6269270.62992247.4536554646269079.55517888
#Sta/Elev= 30
       0    30.9      38    27.9      72   29.01      79   23.17      94   23.11
      97   29.98      99   30.04     198   27.04 206.999    21.2 212.999   25.91
 225.343  23.927 231.787    7.92 237.207    3.77 246.332    3.23 258.395    4.69
 266.135    9.18 269.089  20.524 269.999   24.02 274.999   24.47 284.999    23.7
 285.999   19.96 286.999   22.82 291.999      24 295.999   22.12 353.999   21.32
 439.999   16.76 451.999   12.43 461.999   16.23 549.999   13.07 712.724   20.14
#Mann= 3 , 0 , 0
       0     .03       0 225.343     .03       0 269.089     .03       0
Bank Sta=225.343,269.089
XS Rating Curve= 0 ,0
Exp/Cntr=0.3,0.1

Type RM Length L Ch R = 1 ,2052    ,418.266,369.584,327.346
XS GIS Cut Line= 4
992881.9890869686269342.65523585       992715.12      6269281.59
       992633.04      6269241.08992265.3111253946268993.83932322
#Sta/Elev= 30
       0   27.95       5   25.87      20   25.55      26   28.58      34   25.21
      71   23.13      80   25.62     173   26.77 188.999    16.9 200.609  13.126
 215.427    3.48  239.08    4.45 246.024  11.536 259.999   15.13 262.999   18.34
 274.997   23.21 325.997   19.49 328.997   15.22 331.997   15.16 333.997   12.46
 336.997   12.53 340.997   19.23 411.997   15.69 419.997   12.39 454.997   15.34
 506.997    12.5 576.997   14.63 663.997   13.63 689.997   19.49 712.338   19.46
#Mann= 3 , 0 , 0
       0     .03       0 200.609     .03       0 246.024     .03       0
Bank Sta=200.609,246.024
XS Rating Curve= 0 ,0
Exp/Cntr=0.3,0.1

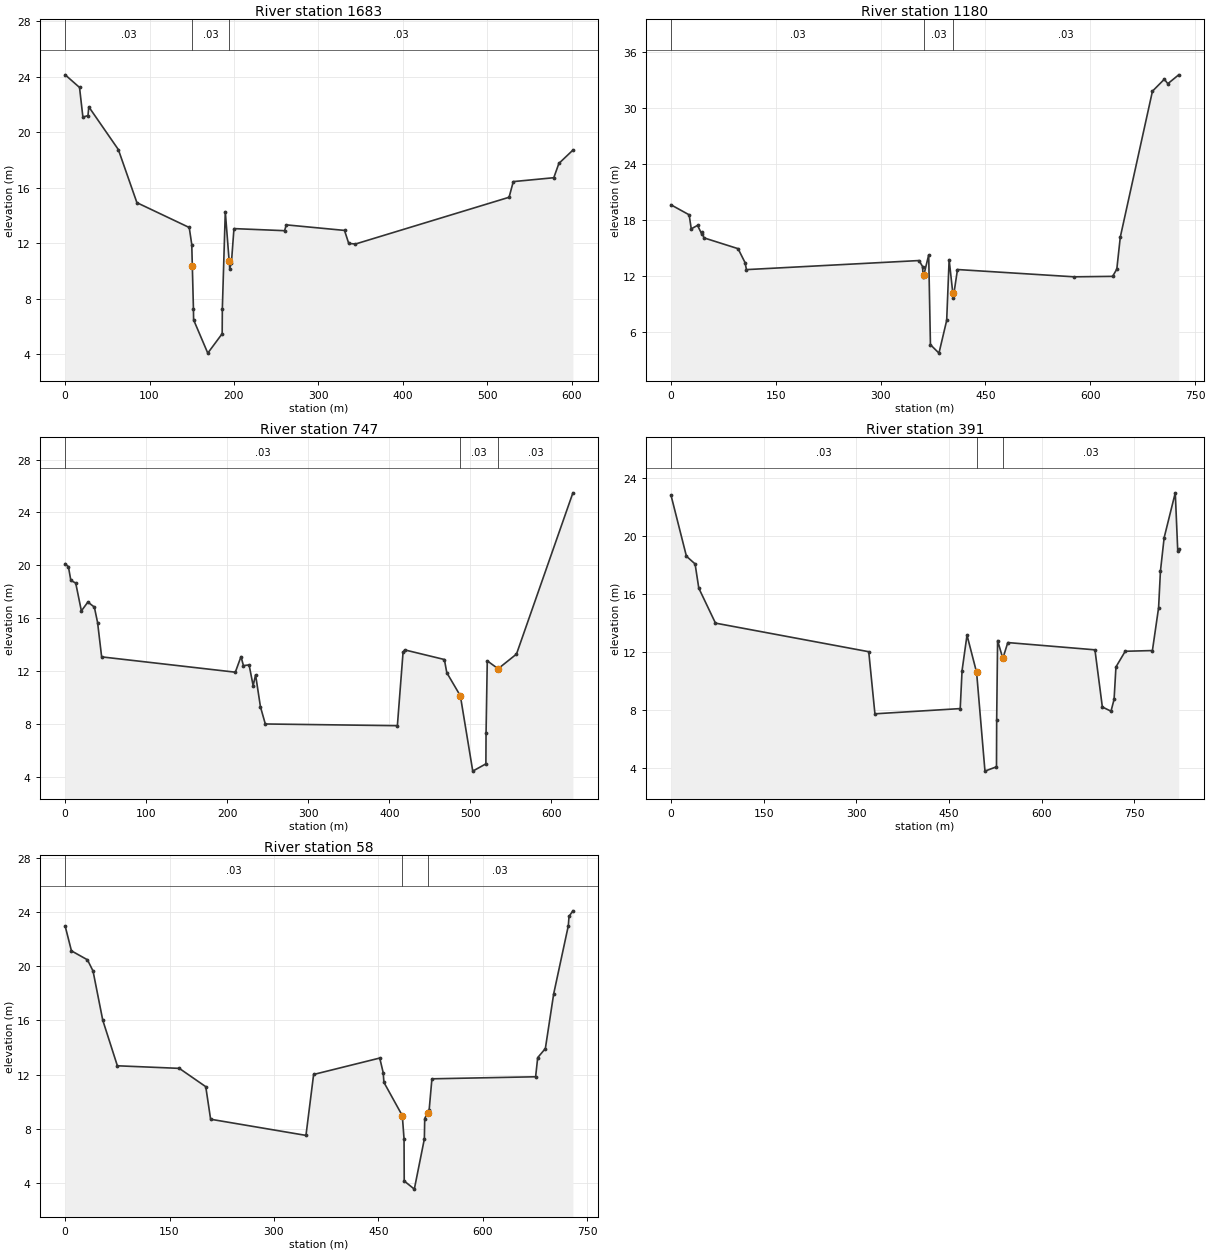
Type RM Length L Ch R = 1 ,1683    ,446.827,502.479,512.602
XS GIS Cut Line= 4
992824.8451831926268870.02753171       992680.43      6268891.32
       992637.94      6268901.77992229.5961855346268955.74338737
#Sta/Elev= 30
       0   24.15      17   23.24      21    21.1      27   21.21      28   21.84
      63   18.76      85   14.93     147   13.14     150   11.91 150.672  10.338
 151.979    7.28 152.185    6.48 168.981    4.08 186.034    5.48  186.23    7.28
 189.733   14.28 194.262  10.754     195   10.18     197   10.61     200   13.06
     260   12.91     262   13.33     331   12.93     336   11.99     344   11.95
     526   15.32     531   16.45     579   16.73     585   17.76 601.628   18.72
#Mann= 3 , 0 , 0
       0     .03       0 150.672     .03       0 194.262     .03       0
Bank Sta=150.672,194.262
XS Rating Curve= 0 ,0
Exp/Cntr=0.3,0.1

Type RM Length L Ch R = 1 ,1180    ,275.347,432.79,516.072
XS GIS Cut Line= 4
992986.752910555 6268515.2591291        992634.7      6268405.39
       992605.54      6268403.14992277.2161053476268391.44733759
#Sta/Elev= 30
       0   19.62      26   18.55      29   17.05      38   17.42      44    16.5
      45   16.68      47   16.09      96   14.93     106   13.44     108   12.69
     355   13.66     360   13.02     361   11.86  361.83  12.115 368.799   14.26
 371.296    4.66 383.492    3.76 394.545    7.26 398.045   13.76 403.339  10.151
     404     9.7     410    12.7     577   11.92     632   11.97     638   12.74
     643   16.17     689   31.77     706   33.05     711   32.57 726.577   33.52
#Mann= 3 , 0 , 0
       0     .03       0  361.83     .03       0 403.339     .03       0
Bank Sta=361.83,403.339
XS Rating Curve= 0 ,0
Exp/Cntr=0.3,0.1

Type RM Length L Ch R = 1 ,747     ,326.674,356.504,328.09
XS GIS Cut Line= 4
993039.1348223496268472.40120127       992771.09      6268068.15
       992768.42      6268032.34992758.1772954556267927.15311942
#Sta/Elev= 30
       0   20.11       4   19.88       7   18.85      13   18.65      20   16.54
      28   17.21      36   16.83      40   15.66      45   13.06     210    11.9
     217   13.08     220    12.4     227   12.45     232   10.88     235    11.7
     241    9.28     247    7.98     410    7.85     417    13.4     419   13.59
     468   12.86     471   11.86 487.747   10.11 503.038    4.41 519.243    4.96
 519.444    7.26 520.948   12.76  534.33   12.16 556.995   13.27 626.632   25.48
#Mann= 3 , 0 , 0
       0     .03       0 487.747     .03       0  534.33     .03       0
Bank Sta=487.747,534.33
XS Rating Curve= 0 ,0
Exp/Cntr=0.3,0.1

Type RM Length L Ch R = 1 ,391     ,299.504,332.834,366.832
XS GIS Cut Line= 4
993253.424461506 6268415.2572975       993108.46      6267949.02
       993096.66      6267910.54 992965.323946646267648.57658851
#Sta/Elev= 30
       0   22.79      25   18.58      39   18.05      45   16.38      72   13.97
     320      12     330    7.72     468    8.08     471    10.7     479   13.14
 494.534  10.572 508.055    3.77 526.703    4.07 527.006    7.27 528.502   12.77
 536.965  11.535     545   12.63     686   12.13     698    8.19     712     7.9
     717    8.72     720   10.95     735   12.03     779   12.08     789   15.03
     792   17.56     798   19.86     816   22.95     820   18.95 821.545   19.07
#Mann= 3 , 0 , 0
       0     .03       0 494.534     .03       0 536.965     .03       0
Bank Sta=494.534,536.965
XS Rating Curve= 0 ,0
Exp/Cntr=0.3,0.1

Type RM Length L Ch R = 1 ,58      ,0,0,0
XS GIS Cut Line= 4
993431.9991608046268336.68442981       993416.12       6267852.5
       993420.65      6267816.58993434.3801567946267608.09965667
#Sta/Elev= 30
       0   22.95       9   21.13      32   20.47      40   19.65      54   16.02
      75   12.66     164   12.47     202   11.12     209    8.72     346    7.53
     357   12.02     452   13.23     457   12.15     458   11.44 484.442   8.987
 486.939    7.27 487.193    4.17 501.706    3.57  516.14    7.27 516.643    8.77
 520.646   9.185 522.995    9.39 526.995    11.7 675.995   11.85 678.995   13.26
 689.995   13.93 701.995   17.97 722.995   22.98 723.995   23.67 729.576   24.08
#Mann= 3 , 0 , 0
       0     .03       0 484.442     .03       0 520.646     .03       0
Bank Sta=484.442,520.646
XS Rating Curve= 0 ,0
Exp/Cntr=0.3,0.1
LCMann Table=0

Chan Stop Cuts=-1
Use User Specified Reach Order=0
Composite Channel Slope=5